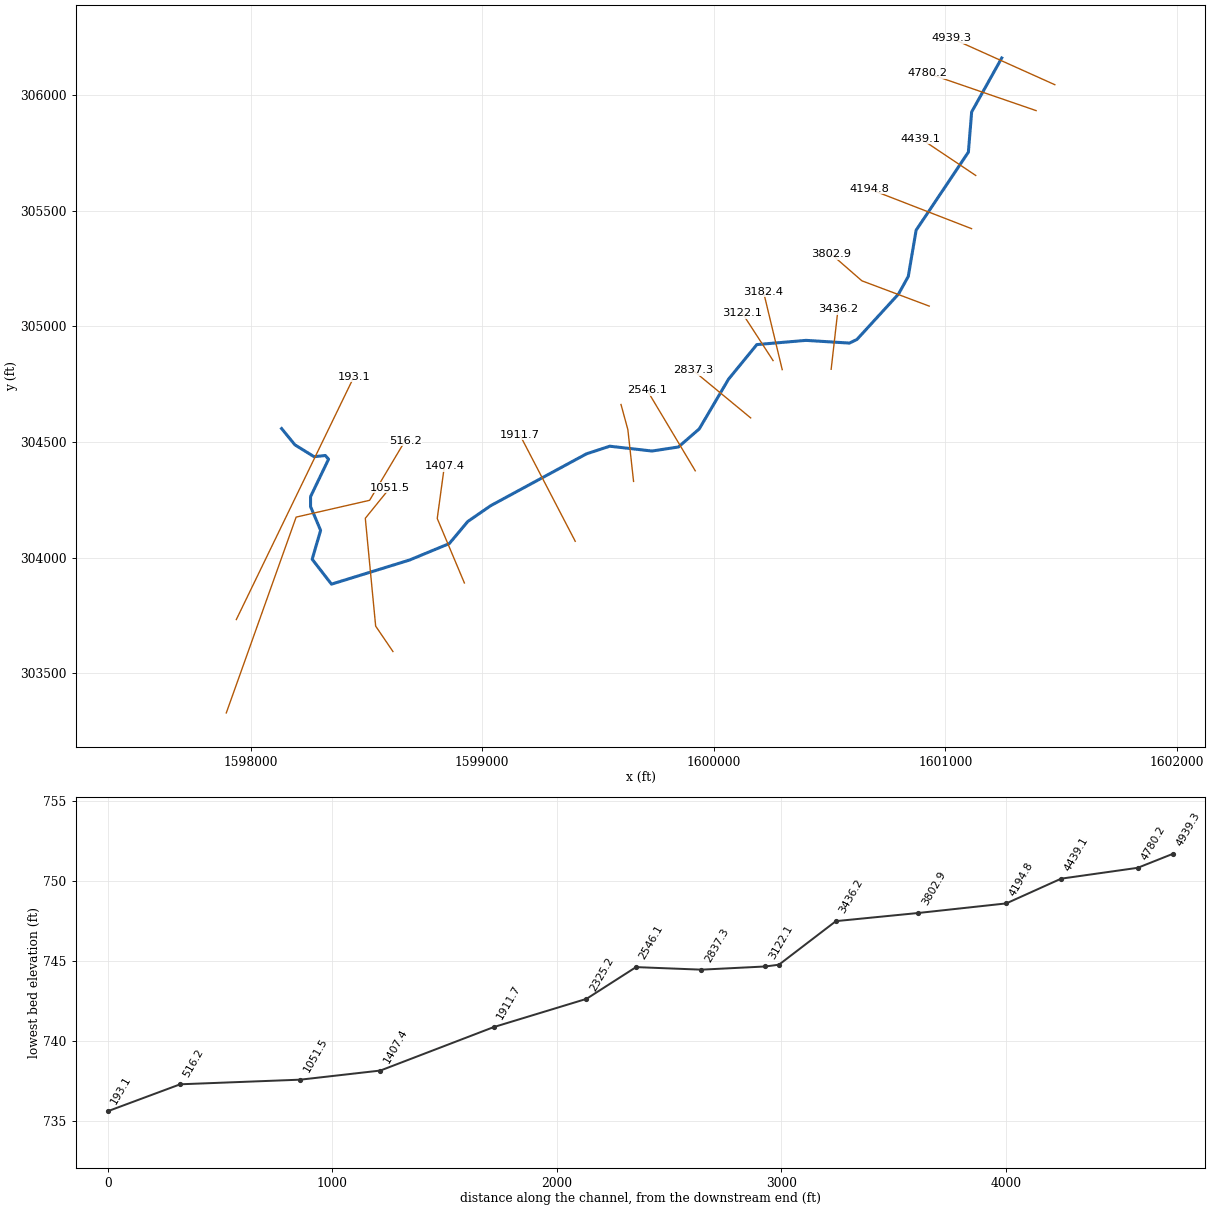
--- NUTTERFRK.prj (project) ---

Proj Title=NUTTERFRK
Current Plan=p01
Default Exp/Contr=0,0
English Units
Geom File=g01
Flow File=f01
Plan File=p01
BEGIN DESCRIPTION:
END DESCRIPTION:
DSS Export Rating Curves= 0
DSS Export Rating Curve Sorted= 0
DSS Export Volume Flow Curves= 0
DXF OffsetX= 0
DXF OffsetY= 0
DXF ScaleX= 0
DXF ScaleY= 0

--- NUTTERFRK.p01 (plan) ---

Plan Title=Floodplain
Program Version=4.00
Geom File=g01
Flow File=f01
K Sum by GR=0
Std Step Tol=0.01
Critical Tol=0.01
Num of Std Step Trials=20
Max Error Tol=0.3
Flow Tol Ratio=0.001
Split Flow NTrial=30
Split Flow Tol=0.02
Split Flow Ratio=0.02
Log Output Level=0
Friction Slope Method=1
Unsteady Friction Slope Method=2
Unsteady Bridges Friction Slope Method=1
Global Log Level=0
CheckData=False
Run HTab=0
Run UNet=0
Run PostProcess=0
UNET Theta=0
UNET Theta Warmup=0
UNET ZTol=0
UNET ZSATol=0
UNET MxIter=0
UNET MaxInSteps=0
UNET DtIC=0
UNET DtMin=0
UNET MaxCRTS=0
UNET WFStab=0
UNET SFStab=0
UNET WFX=0
UNET SFX=0
UNET DSS MLevel=0
UNET DZMax Abort=0
UNET Convert EG Bridges=0
UNET Use Existing IB Tables=0
UNET Froude Limit=0
UNET Froude Power=0
Write IC File=0
Echo Input=False
Echo Output=False
Write Detailed=0

--- NUTTERFRK.f01 (steady flow) ---

Flow Title=NFF Regression Equation
Program Version=4.10
Number of Profiles= 1
Profile Names=P100yr
River Rch & RM=NUTTERFRK,Main            ,4939.3
1843.662
River Rch & RM=NUTTERFRK,Main            ,516.2
1890.464
River Rch & RM=NUTTERFRK,Main            ,193.1
 1891.33
Boundary for River Rch & Prof#=NUTTERFRK,Main            , 1
Up Type= 0
Dn Type= 3
Dn Slope=0.0053
DSS Import GetInterval= 0
DSS Import GetPeak= 0
DSS Import FillOption= 0

--- NUTTERFRK.g01 (geometry) ---

Geom Title=USGS 10m DEM
Program Version=4.10

River Reach=NUTTERFRK       ,Main
Reach XY= 30
     1601243.091      306159.953     1601113.221      305926.621
     1601099.102      305753.009     1600873.408      305415.336
     1600839.554      305215.683     1600797.627      305139.728
     1600617.939      304943.114     1600585.387      304927.489
     1600397.887      304939.207     1600185.648      304920.978
     1600063.252      304771.239      1599936.95      304556.395
     1599847.106       304478.27     1599732.848      304460.764
     1599550.556      304481.597     1599449.862      304448.611
     1599036.582      304224.603     1598937.374      304156.033
     1598857.513      304060.547     1598685.638      303989.366
     1598348.833        303885.2       1598265.5      303992.839
     1598301.958      304117.839     1598258.555      304220.269
     1598258.555      304263.672      1598336.19      304425.391
     1598322.301       304441.45      1598273.69      304436.241
     1598190.847       304487.63      1598133.45      304557.984

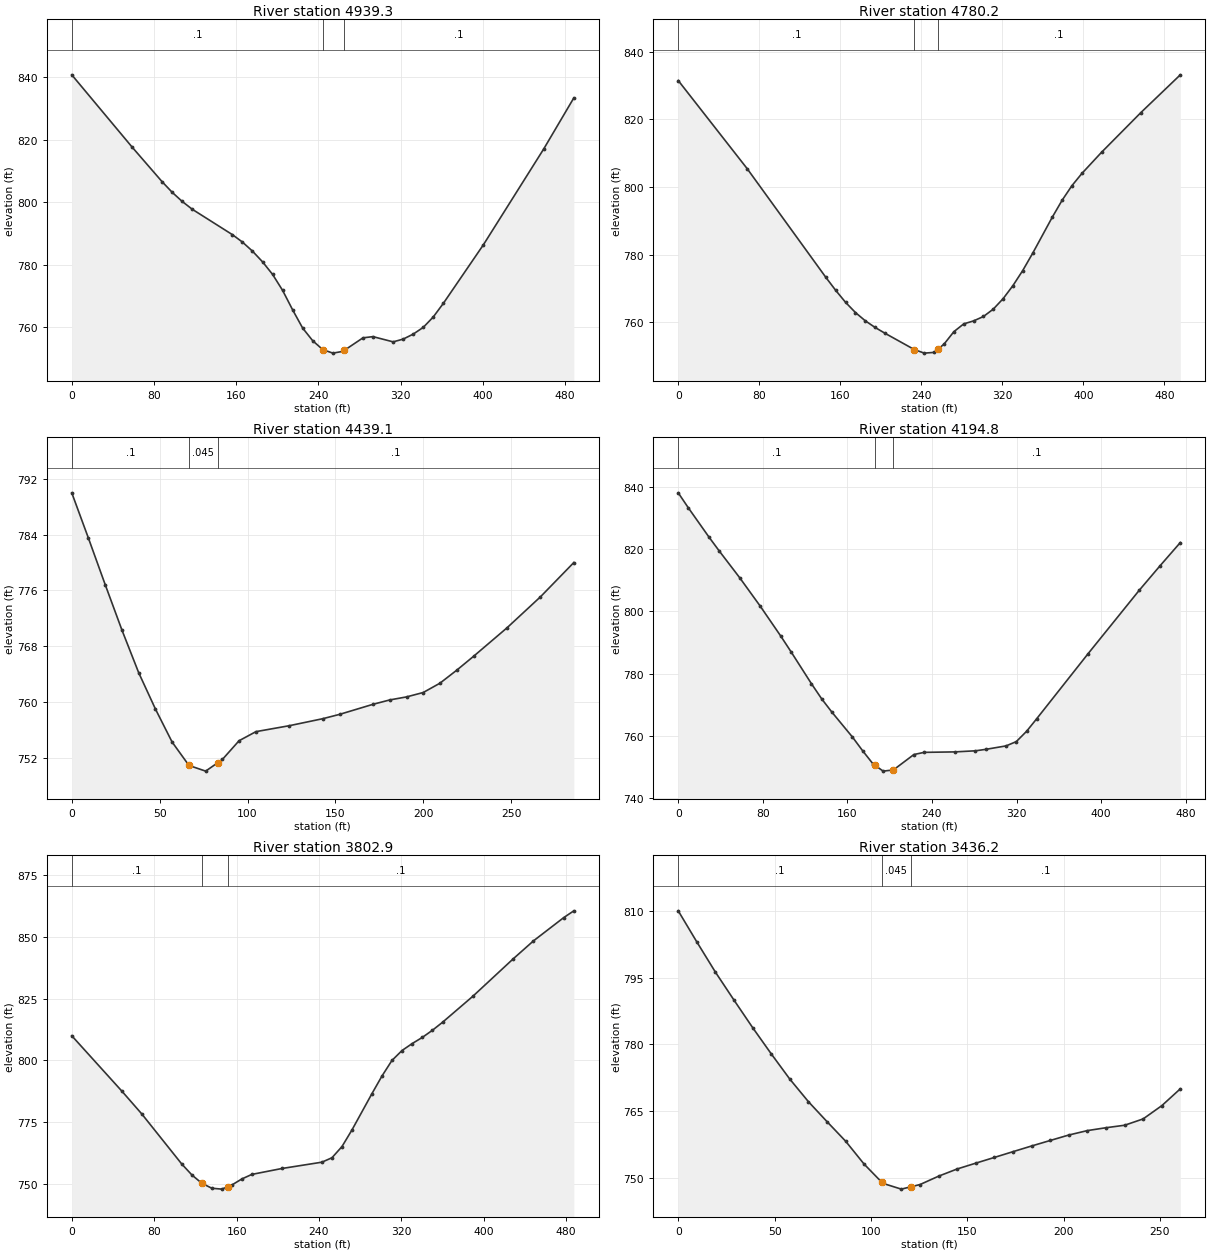
Type RM Length L Ch R = 1 ,4939.3  ,157,159.1,161.1
XS GIS Cut Line= 2
     1601472.279      306044.566     1601026.966      306245.087
#Sta/Elev= 30
       0  840.82    58.6  817.72    87.9  806.59    97.7   803.2   107.4  800.29
   117.2  797.78   156.3  789.64     166  787.28   175.8  784.37   185.6  780.94
   195.4   776.9   205.1   771.8   214.9  765.54   224.6  759.74   234.4  755.68
   244.2  752.84     254  751.72   263.7  752.28   265.3  752.65   283.3  756.62
     293     757   312.6  755.33   322.3   756.2   332.1   757.8   341.9  759.96
   351.6  763.28   361.4  767.63   400.5  786.45   459.1  817.09   488.4  833.44
#Mann= 3 , 0 , 0
       0      .1       0   244.2    .045       0   265.3      .1       0
Bank Sta=244.2,265.3
XS Rating Curve= 0 ,0
Exp/Cntr=0.3,0.1

Type RM Length L Ch R = 1 ,4780.2  ,346.9,341.1,334.9
XS GIS Cut Line= 2
      1601391.55      305932.587       1600922.8      306094.045
#Sta/Elev= 30
       0   831.5      68  805.45   145.8  773.24   155.5  769.41   165.3  765.84
     175  762.84   184.7   760.4   194.4  758.43   204.1  756.72   233.3  751.86
     243  750.83   252.8  751.05   256.4  751.96   262.5  753.51   272.2  757.18
   281.9  759.48   291.6  760.36   301.4  761.67   311.1  763.85   320.8  766.94
   330.5   770.8   340.2  775.28     350  780.38   369.4  791.08   379.1  796.08
   388.8   800.4   398.6     804     418  810.26   456.9  822.03   495.8  833.19
#Mann= 3 , 0 , 0
       0      .1       0   233.3    .045       0   256.4      .1       0
Bank Sta=233.3,256.4
XS Rating Curve= 0 ,0
Exp/Cntr=0.3,0.1

Type RM Length L Ch R = 1 ,4439.1  ,239.2,244.3,249.6
XS GIS Cut Line= 2
     1601130.826      305652.212     1600893.447        305811.2
#Sta/Elev= 26
       0  789.97     9.5  783.47      19  776.85    28.6   770.3    38.1  764.22
    47.6  759.04    57.1  754.31    66.7  750.96    76.2  750.15    83.1  751.36
    85.7  751.82    95.2   754.5   104.8   755.8   123.8  756.65   142.8  757.65
   152.4  758.27   171.4  759.71     181  760.34   190.5  760.77     200   761.4
   209.5  762.73     219  764.58   228.6  766.57   247.6  770.64   266.7  775.09
   285.7     780
#Mann= 3 , 0 , 0
       0      .1       0    66.7    .045       0    83.1      .1       0
Bank Sta=66.7,83.1
XS Rating Curve= 0 ,0
Exp/Cntr=0.3,0.1

Type RM Length L Ch R = 1 ,4194.8  ,391.3,391.9,392.5
XS GIS Cut Line= 2
     1601112.904       305422.17     1600670.196      305594.045
#Sta/Elev= 30
       0  838.16     9.7  833.26    29.1  823.91    38.8  819.44    58.2  810.81
    77.5  801.72    96.9   792.1   106.6  787.06     126  776.73   135.7  771.85
   145.4  767.56   164.8  759.56   174.4  755.16   184.2  750.94   186.1  750.48
   193.8   748.6   203.5  748.98   222.9  753.94   232.6  754.64   261.7  754.79
   281.1  755.14   290.8   755.6   310.1  756.72   319.8  758.11   329.5  761.42
   339.2  765.52   387.7  786.41   436.1  806.82   455.5  814.59   474.9  822.16
#Mann= 3 , 0 , 0
       0      .1       0   186.1    .045       0   203.5      .1       0
Bank Sta=186.1,203.5
XS Rating Curve= 0 ,0
Exp/Cntr=0.3,0.1

Type RM Length L Ch R = 1 ,3802.9  ,397.1,366.7,335.6
XS GIS Cut Line= 3
     1600930.081      305087.298     1600639.132      305196.713
     1600506.133      305312.795
#Sta/Elev= 30
       0     810    48.6  787.63      68  778.38   106.8  758.14   116.6  753.74
   126.3  750.35     136  748.36   145.7     748   151.2  748.95   155.4  749.67
   165.1  752.11   174.8  753.95     204  756.34   242.8  758.89   252.6  760.69
   262.3   765.2     272  771.92   291.4   786.6   301.1   793.7   310.8  800.01
   320.6  804.03   330.5  806.85   340.3  809.33   350.1  812.21   359.9  815.44
   389.3  825.94   428.5  841.08   448.2  848.35   477.6  857.77   487.4   860.5
#Mann= 3 , 0 , 0
       0      .1       0   126.3    .045       0   151.2      .1       0
Bank Sta=126.3,151.2
XS Rating Curve= 0 ,0
Exp/Cntr=0.3,0.1

Type RM Length L Ch R = 1 ,3436.2  ,245.8,253.8,261.7
XS GIS Cut Line= 2
     1600506.593      304814.446     1600536.046      305073.423
#Sta/Elev= 30
       0     810     9.6  803.05    19.3  796.23      29  789.91    38.6  783.78
    48.3  777.86    57.9  772.21    67.6  767.12    77.2  762.66    86.9  758.25
    96.5   753.1   105.6  749.06   106.2  748.79   115.8  747.49   120.6     748
   125.5  748.52   135.2  750.41   144.8  752.02   154.5  753.33   164.1  754.61
   173.8  755.91   183.4  757.18   193.1  758.42   202.7  759.64   212.4  760.64
     222  761.28   231.7  761.84   241.3  763.26     251  766.24   260.6  770.02
#Mann= 3 , 0 , 0
       0      .1       0   105.6    .045       0   120.6      .1       0
Bank Sta=105.6,120.6
XS Rating Curve= 0 ,0
Exp/Cntr=0.3,0.1

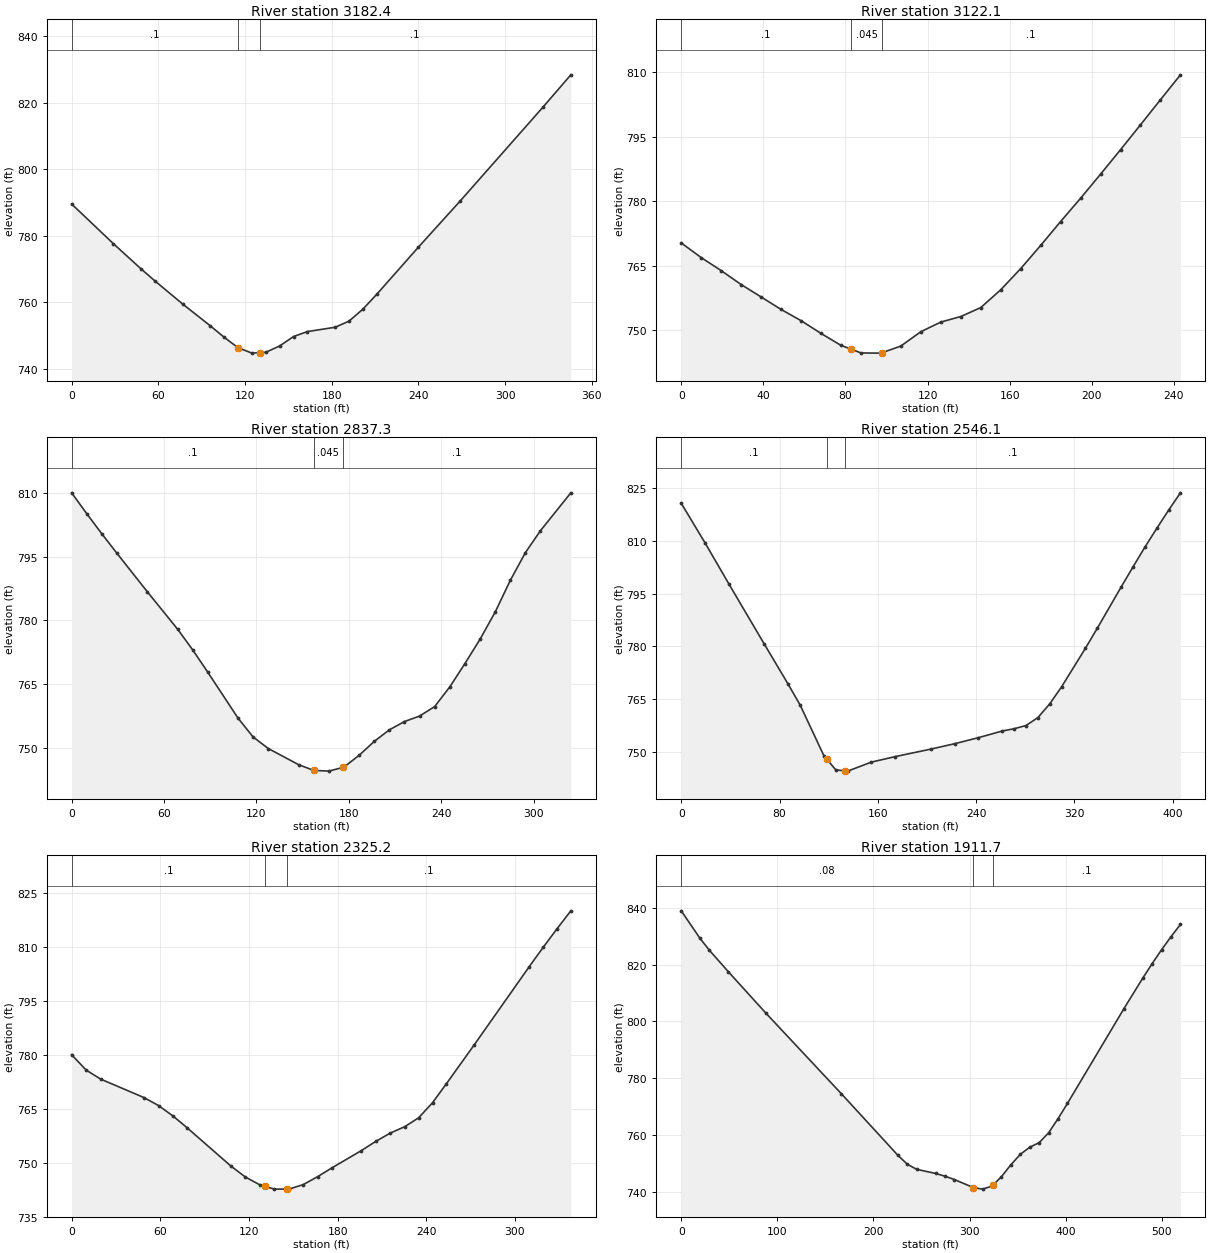
Type RM Length L Ch R = 1 ,3182.4  ,51.9,60.3,68.1
XS GIS Cut Line= 2
     1600295.196      304812.795     1600214.466      305148.732
#Sta/Elev= 22
       0  789.54    28.8  777.67      48  770.08    57.6  766.46    76.8  759.53
      96  752.95   105.6  749.51   115.1   746.4   124.8  744.76   130.1   744.9
   134.4  745.02     144  746.92   153.6  749.75   163.2  751.23   182.4  752.53
     192  754.37   201.5  757.93   211.1  762.39   239.9  776.53   268.7  790.34
   326.3  818.67   345.5  828.33
#Mann= 3 , 0 , 0
       0      .1       0   115.1    .045       0   130.1      .1       0
Bank Sta=115.1,130.1
XS Rating Curve= 0 ,0
Exp/Cntr=0.3,0.1

Type RM Length L Ch R = 1 ,3122.1  ,278.5,284.8,291.7
XS GIS Cut Line= 2
     1600255.699      304851.857     1600123.321      305055.851
#Sta/Elev= 28
       0  770.26     9.7  766.87    19.4  763.85    29.2  760.59    38.9  757.71
    48.6  754.82    58.4  752.19    68.1  749.23    77.8  746.46    82.8  745.56
    87.6  744.69    97.3  744.65    97.8  744.74     107   746.3   116.7  749.62
   126.4  751.86   136.2  753.16   145.9  755.23   155.6  759.35   165.4  764.31
   175.1  769.68   184.8  775.23   194.6  780.68   204.3  786.26     214  791.93
   223.7   797.7   233.4  803.52   243.2  809.34
#Mann= 3 , 0 , 0
       0      .1       0    82.8    .045       0    97.8      .1       0
Bank Sta=82.8,97.8
XS Rating Curve= 0 ,0
Exp/Cntr=0.3,0.1

Type RM Length L Ch R = 1 ,2837.3  ,298.9,291.2,283.5
XS GIS Cut Line= 2
      1600159.11      304603.913     1599909.207      304810.264
#Sta/Elev= 30
       0     810     9.8   805.1    19.6  800.35    29.5  795.72    49.1  786.72
    68.8  777.89    78.6  773.01    88.4  767.75     108  756.95   117.8   752.5
   127.7  749.77   147.3  745.98   157.1  744.63     167  744.45   176.1  745.33
   176.8   745.4   186.6  748.16   196.4  751.43   206.2  754.16   216.1  756.13
   225.9  757.42   235.7  759.66   245.5  764.28   255.3  769.76   265.2  775.54
     275  781.93   284.8  789.38   294.6  795.92   304.4  801.09   324.1     810
#Mann= 3 , 0 , 0
       0      .1       0   157.1    .045       0   176.1      .1       0
Bank Sta=157.1,176.1
XS Rating Curve= 0 ,0
Exp/Cntr=0.3,0.1

Type RM Length L Ch R = 1 ,2546.1  ,230.4,220.9,211
XS GIS Cut Line= 2
     1599919.675      304375.295     1599711.341      304724.253
#Sta/Elev= 30
       0  820.59    19.4  809.35    38.7  797.76    67.7   780.6    87.1  769.24
    96.8  763.35   116.1     749   118.5     748   125.8  744.96   133.5  744.68
   135.5  744.61   154.8  747.17   174.2  748.73   203.2  750.86   222.6  752.39
   241.9   754.1   261.3  755.99   270.9  756.63   280.6  757.54   290.3  759.78
     300   763.7   309.6  768.51     329  779.44   338.7  785.14     358  796.77
   367.7  802.51   377.4  808.12   387.1  813.46   396.7  818.62   406.4  823.56
#Mann= 3 , 0 , 0
       0      .1       0   118.5    .045       0   133.5      .1       0
Bank Sta=118.5,133.5
XS Rating Curve= 0 ,0
Exp/Cntr=0.3,0.1

Type RM Length L Ch R = 1 ,2325.2  ,404.8,413.5,422.5
XS GIS Cut Line= 3
     1599653.305      304329.434     1599628.609      304553.533
     1599599.099      304661.961
#Sta/Elev= 29
       0     780     9.8  775.73    19.6  773.22      49  768.07    58.8  765.86
    68.6  762.95    78.4  759.59   107.8  749.03   117.6  745.98   127.4   743.8
   130.9  743.38   137.2  742.63   145.9  742.62     147  742.62   156.8  743.89
   166.6  746.12   176.4   748.6     196  753.32   205.8   755.9   215.6   758.2
   225.5     760   234.8  762.45   244.2  766.64   253.6  771.93   272.3  782.66
   309.7  804.51   319.1  809.86   328.5  815.04   337.8     820
#Mann= 3 , 0 , 0
       0      .1       0   130.9    .045       0   145.9      .1       0
Bank Sta=130.9,145.9
XS Rating Curve= 0 ,0
Exp/Cntr=0.3,0.1

Type RM Length L Ch R = 1 ,1911.7  ,506.2,504.3,502.2
XS GIS Cut Line= 2
     1599401.446      304070.607     1599161.862      304531.545
#Sta/Elev= 30
       0  838.99    19.6  829.25    29.4  825.04      49  817.52    88.2  802.87
   166.6   774.5   225.4   752.8   235.2  749.64     245  747.83   264.6  746.38
   274.4  745.42   284.2  744.24   303.8  741.42   313.6  740.85   323.4  741.92
   324.3  742.22   333.2  745.23   343.1  749.47   352.9  753.14   362.7  755.63
   372.5  757.26   382.3  760.72   392.1  765.69   401.9  771.08   460.7  804.51
   480.3  815.27   490.1  820.41   499.9  825.29   509.7  829.89   519.5  834.19
#Mann= 3 , 0 , 0
       0     .08       0   303.8    .045       0   324.3      .1       0
Bank Sta=303.8,324.3
XS Rating Curve= 0 ,0
Exp/Cntr=0.3,0.1

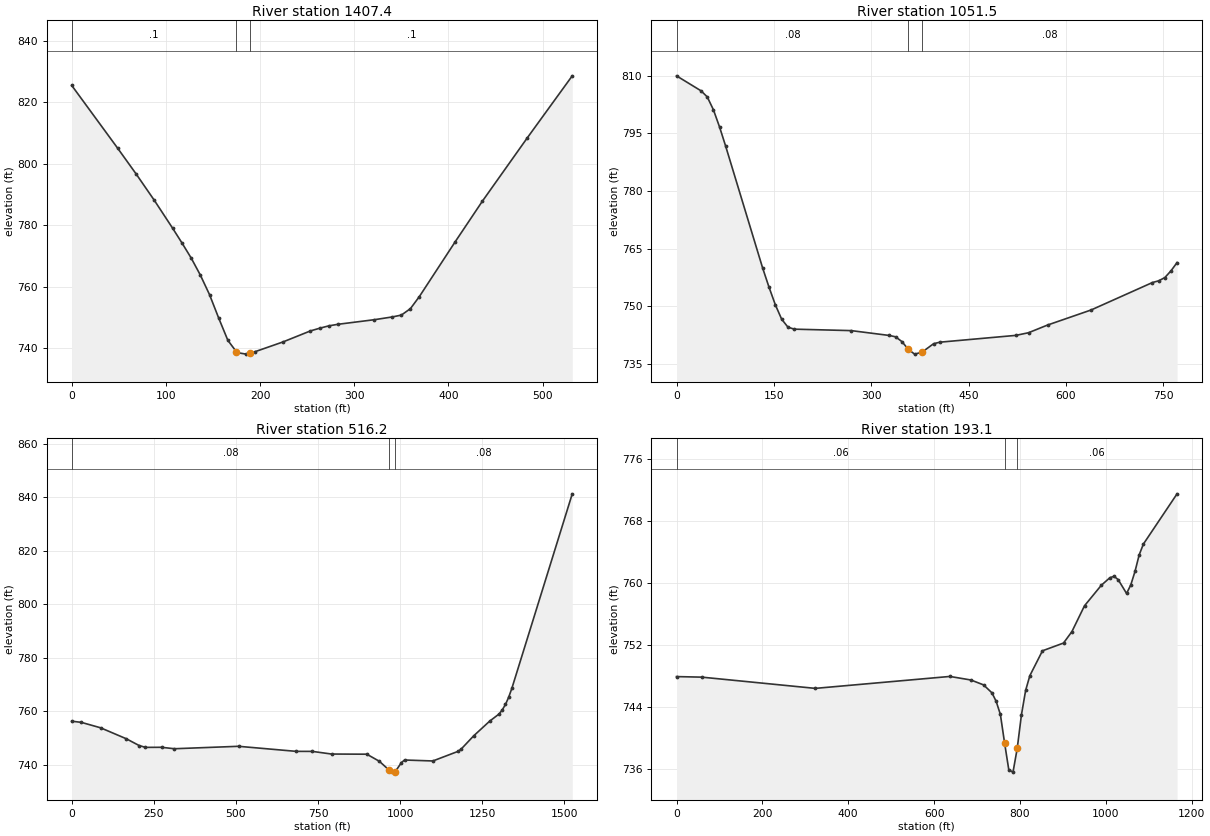
Type RM Length L Ch R = 1 ,1407.4  ,362.7,355.9,348.9
XS GIS Cut Line= 3
     1598922.713      303890.486     1598805.525      304169.132
     1598836.428      304396.128
#Sta/Elev= 30
       0  825.45    48.8  805.04    68.3  796.72    87.8  788.07   107.3  778.97
     117  774.29   126.8  769.38   136.5  763.86   146.3  757.48     156  749.89
   165.8   742.6   174.7  738.95   175.5  738.62   185.3  738.13   189.7  738.51
     195  738.96   224.3  742.09   253.5  745.68   263.3  746.55     273  747.32
   282.8  747.83   321.4  749.32   340.5  750.22     350  750.82   359.6  752.91
   369.1  756.84   407.3  774.72   435.9  787.79   483.6  808.38   531.4  828.56
#Mann= 3 , 0 , 0
       0      .1       0   174.7    .045       0   189.7      .1       0
Bank Sta=174.7,189.7
XS Rating Curve= 0 ,0
Exp/Cntr=0.3,0.1

Type RM Length L Ch R = 1 ,1051.5  ,569.4,535.4,500.9
XS GIS Cut Line= 4
     1598614.286      303593.989     1598539.624      303703.744
     1598494.904      304169.949     1598601.966      304302.378
#Sta/Elev= 30
       0     810    37.9  806.09    47.4  804.51    56.9  801.16    66.4  796.66
    75.8  791.67   132.7     760   142.5  755.02   152.3  750.41     162  746.67
   171.8  744.57   181.5  744.06   269.3  743.68   327.9  742.42   337.6  742.07
   347.4  740.82   357.2  738.82   366.9  737.56   378.2  738.05   396.2  740.27
   405.9  740.67     523  742.44   542.5  743.13   571.8  745.13   638.9  749.05
   733.5   756.2     743  756.64   752.5  757.48   761.9  759.21   771.4   761.4
#Mann= 3 , 0 , 0
       0     .08       0   357.2    .045       0   378.2     .08       0
Bank Sta=357.2,378.2
XS Rating Curve= 0 ,0
Exp/Cntr=0.3,0.1

Type RM Length L Ch R = 1 ,516.2   ,300.2,323.1,341.1
XS GIS Cut Line= 4
     1597894.588       303328.42     1598196.177      304175.039
     1598513.425      304247.691     1598667.071      304505.503
#Sta/Elev= 30
       0   756.3    29.3  755.87    87.9  753.84   166.1  749.75   205.2  747.22
   224.7  746.52   273.5  746.55   312.6  746.01     508  746.92   683.8  745.03
   732.7  745.02   791.3  744.03   898.7  743.97     937  741.31   966.3  738.06
   975.3  737.27   984.9  737.37    1004  740.83  1013.6   741.8  1099.8  741.44
  1176.3  745.02  1185.9  745.87  1224.2  750.84  1272.6   756.3  1301.6  759.01
  1311.3  760.56    1321  762.57  1330.7  765.26  1340.4  768.59  1524.3  841.27
#Mann= 3 , 0 , 0
       0     .08       0   966.3    .045       0   984.9     .08       0
Bank Sta=966.3,984.9
XS Rating Curve= 0 ,0
Exp/Cntr=0.3,0.1

Type RM Length L Ch R = 1 ,193.1   ,202.7,193.1,185.9
XS GIS Cut Line= 2
     1597937.904      303732.066     1598445.716      304781.545
#Sta/Elev= 30
       0  747.91    58.8  747.84   323.3  746.39   636.8  747.93   685.8  747.47
   715.2  746.84   734.8  745.81   744.6  744.71   754.4  743.02   764.2  739.33
     774  735.87   783.8  735.58   793.6  738.64   803.4  742.97   813.2  746.13
     823  748.03   852.4  751.24   901.4  752.24     921  753.72   950.3  757.05
   989.5   759.7  1009.1  760.66  1018.9  760.86  1028.7  760.43  1048.3  758.64
  1058.1  759.74  1067.9  761.48  1077.7  763.63  1087.5  765.02  1165.9   771.5
#Mann= 3 , 0 , 0
       0     .06       0   764.2    .045       0   793.6     .06       0
Bank Sta=764.2,793.6
XS Rating Curve= 0 ,0
Exp/Cntr=0.3,0.1

Chan Stop Cuts=-1
Use User Specified Reach Order=0
Composite Channel Slope=5